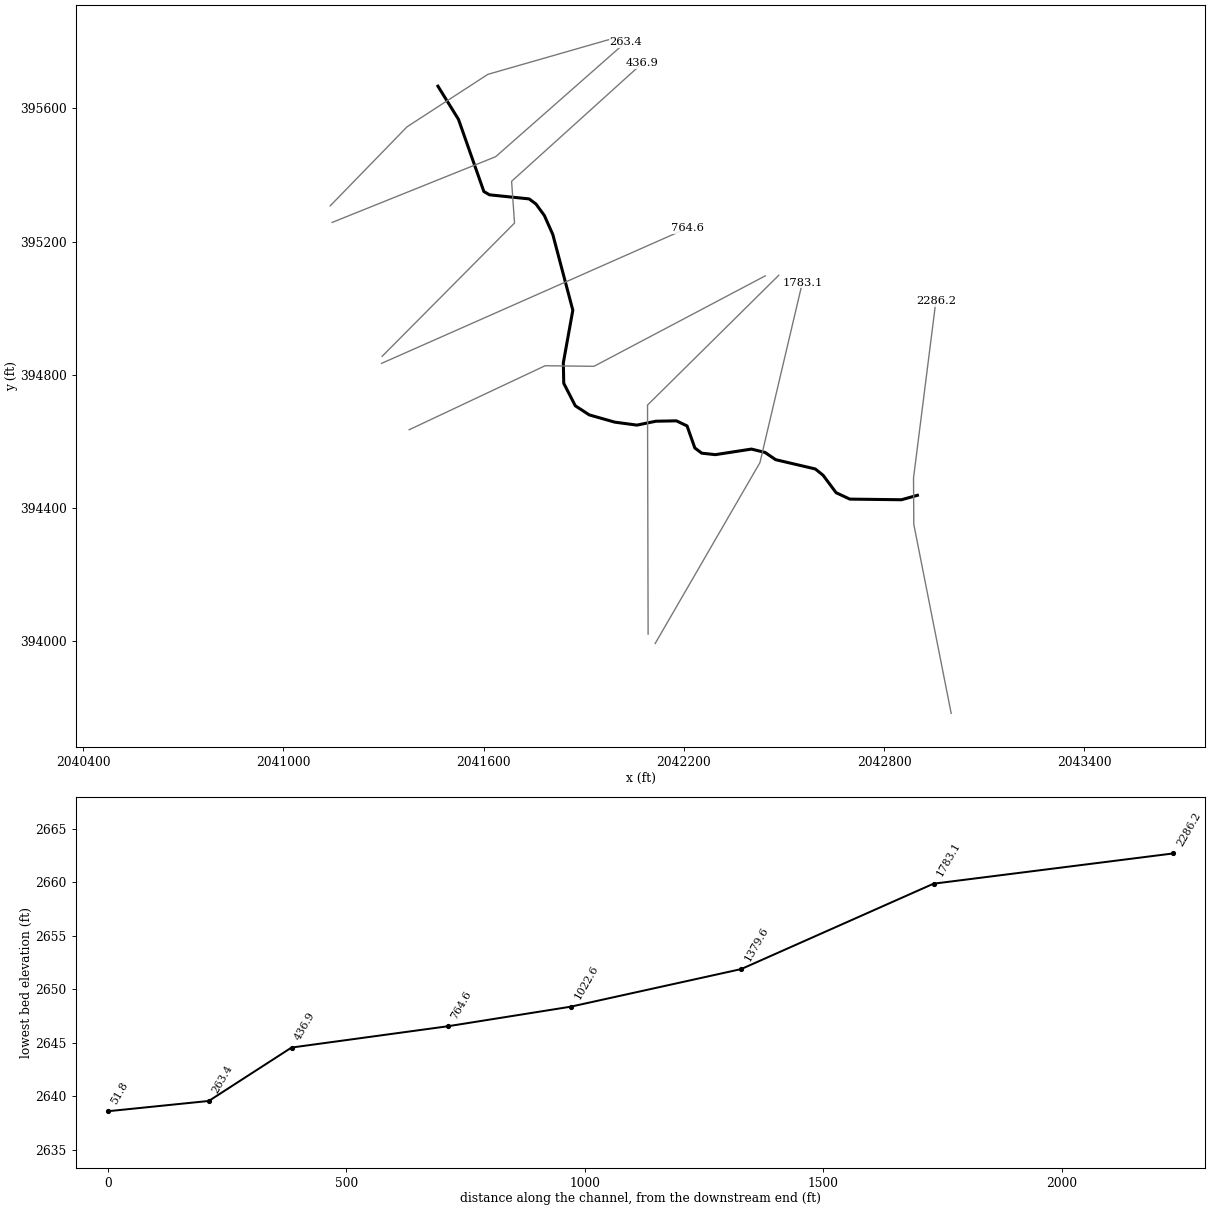
--- AnglinsCr.prj (project) ---

Proj Title=AnglinsCr
Current Plan=p01
Default Exp/Contr=0,0
English Units
Geom File=g01
Flow File=f01
Plan File=p01
BEGIN DESCRIPTION:
END DESCRIPTION:
DSS Export Rating Curves= 0
DSS Export Rating Curve Sorted= 0
DSS Export Volume Flow Curves= 0
DXF OffsetX= 0
DXF OffsetY= 0
DXF ScaleX= 0
DXF ScaleY= 0

--- AnglinsCr.p01 (plan) ---

Plan Title=Floodplain
Program Version=4.00
Geom File=g01
Flow File=f01
K Sum by GR=0
Std Step Tol=0.01
Critical Tol=0.01
Num of Std Step Trials=20
Max Error Tol=0.3
Flow Tol Ratio=0.001
Split Flow NTrial=30
Split Flow Tol=0.02
Split Flow Ratio=0.02
Log Output Level=0
Friction Slope Method=1
Unsteady Friction Slope Method=2
Unsteady Bridges Friction Slope Method=1
Global Log Level=0
CheckData=False
Run HTab=0
Run UNet=0
Run PostProcess=0
UNET Theta=0
UNET Theta Warmup=0
UNET ZTol=0
UNET ZSATol=0
UNET MxIter=0
UNET MaxInSteps=0
UNET DtIC=0
UNET DtMin=0
UNET MaxCRTS=0
UNET WFStab=0
UNET SFStab=0
UNET WFX=0
UNET SFX=0
UNET DSS MLevel=0
UNET DZMax Abort=0
UNET Convert EG Bridges=0
UNET Use Existing IB Tables=0
UNET Froude Limit=0
UNET Froude Power=0
Write IC File=0
Echo Input=False
Echo Output=False
Write Detailed=0

--- AnglinsCr.f01 (steady flow) ---

Flow Title=Moglen and others (2006)
Program Version=4.00
Number of Profiles=1
Profile Names=P100yr
River Rch & RM=AnglinsCr,Main      ,2286.2
749.3732
River Rch & RM=AnglinsCr,Main      ,263.4
796.1442
Boundary for River Rch & Prof#=AnglinsCr,Main      ,1
Up Type=0
Dn Type=3
Dn Slope=0.013126

--- AnglinsCr.g01 (geometry) ---

Geom Title=USGS 10m DEM
Program Version=4.10

River Reach=AnglinsCr       ,Main
Reach XY= 30
      2042899.94      394438.374     2042852.025         394425.
     2042697.206      394426.918     2042656.163      394446.205
     2042617.289      394498.471     2042593.852      394517.444
     2042474.996      394545.344      2042443.19      394567.107
     2042402.455      394577.151     2042294.201       394560.41
     2042253.467      394564.875      2042232.82      394580.499
     2042209.518      394646.721     2042177.578      394661.968
     2042116.197      394660.852      2042059.28      394649.134
     2041992.877      394658.062     2041916.429      394679.824
     2041874.579      394707.167     2041839.982      394774.686
     2041838.738      394836.324     2041867.163      394994.241
     2041807.155      395221.641     2041781.888      395278.491
     2041756.621      395313.233     2041736.299      395328.475
     2041617.708      395340.693     2041600.596      395350.551
     2041524.521      395567.245     2041462.896      395666.967

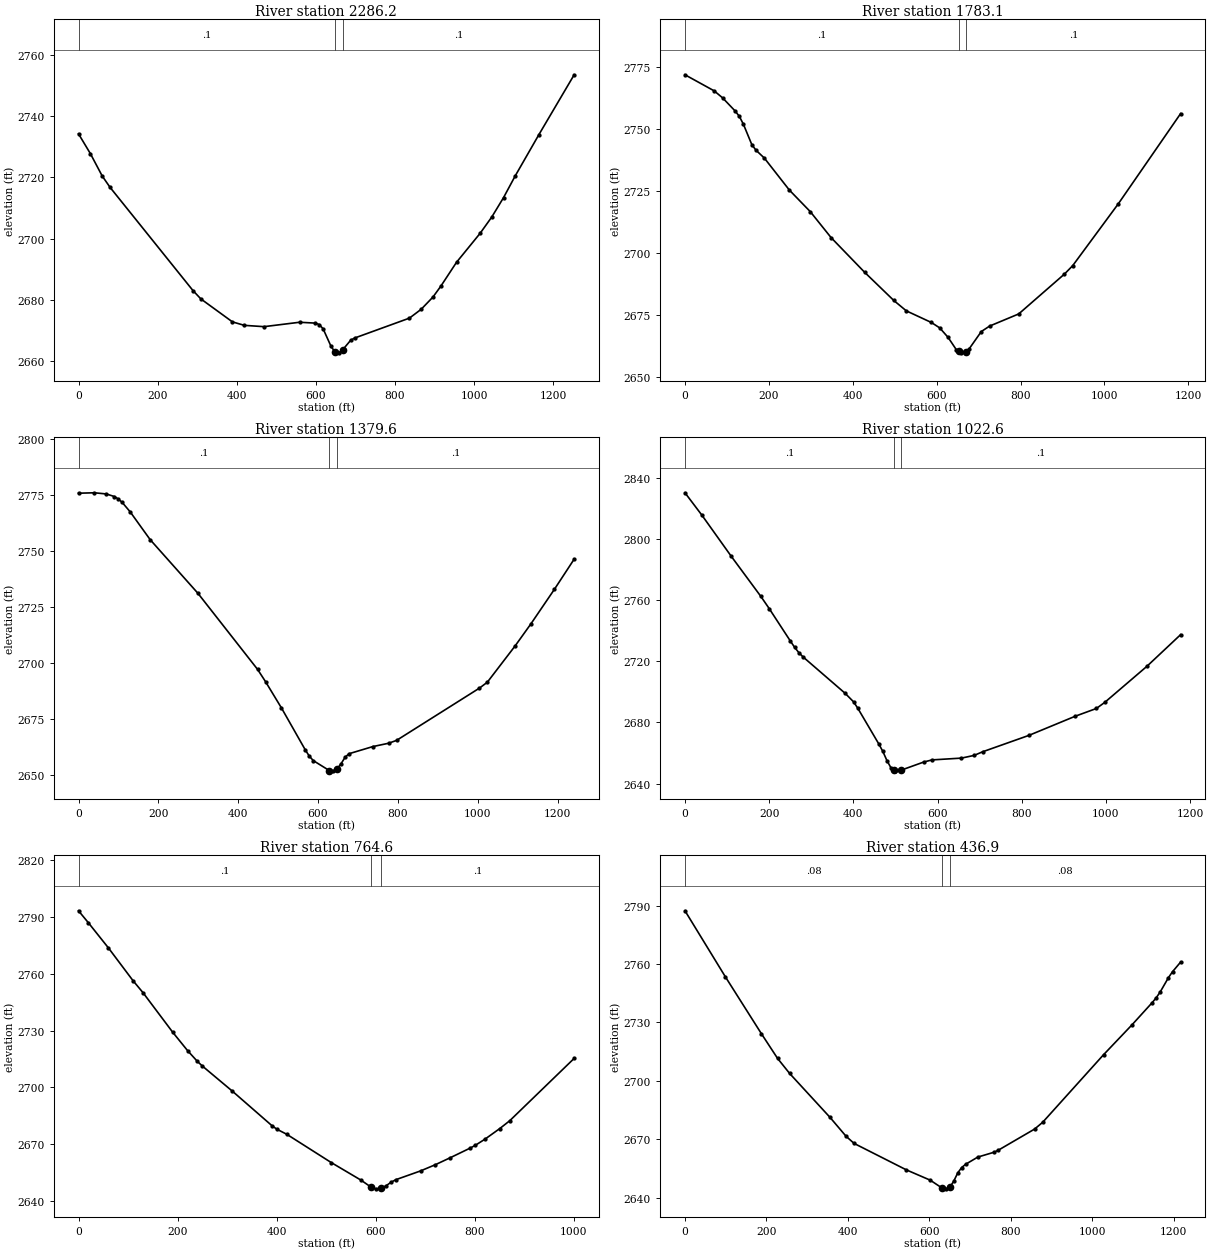
Type RM Length L Ch R = 1 ,2286.2  ,509.4,503.1,495.7
XS GIS Cut Line= 4
     2043001.067      393783.449     2042889.018      394351.328
     2042888.198      394490.156     2042955.214      395021.485
#Sta/Elev= 30
       0 2734.23    29.9 2727.79    59.9 2720.46    79.8 2716.74   289.4 2683.03
   309.4  2680.3   389.2  2672.8   419.2 2671.67     469 2671.24   558.9 2672.68
   598.7  2672.4   608.6 2671.94   618.5 2670.52   638.3 2664.86   648.2 2662.99
   658.2 2662.69   668.2 2663.73   687.9 2666.77   697.8 2667.51   836.7 2674.03
   866.4 2676.92   896.2 2680.92     916 2684.45   955.7 2692.26  1015.2  2701.7
  1044.9 2707.06  1074.7 2713.41  1104.4 2720.55  1163.9 2733.94  1253.2 2753.52
#Mann= 3 , 0 , 0
       0      .1       0   648.2    .045       0   668.2      .1       0
Bank Sta=648.2,668.2
XS Rating Curve= 0 ,0
Exp/Cntr=0.3,0.1

Type RM Length L Ch R = 1 ,1783.1  ,395.2,403.4,411.5
XS GIS Cut Line= 3
     2042113.984      393993.315     2042427.902      394536.499
     2042554.881      395076.156
#Sta/Elev= 30
       0 2771.81    69.7 2765.33    89.6 2762.53   119.5 2757.25   129.5  2755.1
   139.4 2751.86   159.3 2743.72   169.3 2741.44   189.2 2738.28     249 2725.37
   298.8  2716.7   348.5 2706.23   428.2 2692.32   497.9 2680.94   527.8 2676.76
   587.5 2672.08   607.4  2669.9   627.4 2666.07   647.1 2661.09  652.35 2660.41
   657.1 2659.86   670.1 2660.35   676.9 2661.31   706.6 2668.44   726.4 2670.64
   795.7 2675.52   904.6 2691.55   924.4 2694.95  1033.3 2719.89  1181.8 2756.19
#Mann= 3 , 0 , 0
       0      .1       0  652.35    .045       0   670.1      .1       0
Bank Sta=652.35,670.1
XS Rating Curve= 0 ,0
Exp/Cntr=0.3,0.1

Type RM Length L Ch R = 1 ,1379.6  ,405.3,357.1,308.8
XS GIS Cut Line= 3
     2042092.821      394021.533     2042091.058       394709.33
     2042484.337      395099.083
#Sta/Elev= 30
       0 2775.71    39.9  2775.9    69.8 2775.37    89.7 2774.23    99.7 2773.14
   109.6 2771.57   129.6 2767.35   179.4 2755.01     299 2731.09   448.6 2697.11
   468.5 2691.64   508.4 2679.91   568.2 2661.17   578.2 2658.41   588.1 2656.44
     628 2652.03     638 2651.88     648 2652.83   657.9 2655.13   667.9 2657.99
   677.8 2659.53   737.2  2662.7   776.8 2664.19   796.6 2665.46  1004.2 2688.77
    1024 2691.41  1093.2  2707.5  1132.7 2717.32  1192.1 2732.87  1241.5  2746.3
#Mann= 3 , 0 , 0
       0      .1       0     628    .045       0     648      .1       0
Bank Sta=628,648
XS Rating Curve= 0 ,0
Exp/Cntr=0.3,0.1

Type RM Length L Ch R = 1 ,1022.6  ,244.9,257.9,271
XS GIS Cut Line= 4
     2041376.806       394635.26     2041784.194      394827.491
     2041930.572      394825.727     2042443.775      395097.319
#Sta/Elev= 30
       0 2830.05      40 2815.49   110.1 2788.48   180.2 2762.36   200.2 2754.34
   250.3 2733.21   260.3 2729.14   270.3 2725.66   280.3 2722.85   380.4 2699.05
   400.4 2693.49   410.4 2689.34   460.2 2666.06     470 2661.08   479.7 2655.12
   489.3 2650.37  496.06 2648.98   499.3 2648.37  512.47 2648.71   567.6 2654.16
   587.1 2655.52   656.9 2656.69     687 2658.46     707 2660.81   817.1 2671.54
   927.2 2684.06   977.3 2689.11   997.3 2693.11  1097.4 2716.67  1177.5 2737.36
#Mann= 3 , 0 , 0
       0      .1       0  496.06    .045       0  512.47      .1       0
Bank Sta=496.06,512.47
XS Rating Curve= 0 ,0
Exp/Cntr=0.3,0.1

Type RM Length L Ch R = 1 ,764.6   ,290.4,327.7,364.8
XS GIS Cut Line= 2
     2041293.918      394834.545     2042209.218      395240.169
#Sta/Elev= 30
       0 2793.19      20 2786.85    60.1 2773.71   110.1 2756.33   130.2 2750.03
   190.2 2729.16   220.2 2719.47   240.3  2713.7   250.3 2711.28   310.4 2698.14
   390.4 2679.93   400.5 2678.01   420.5 2675.34   510.6 2660.39   570.7 2651.11
   590.7 2647.48   600.7 2646.54   610.7 2646.77   620.7 2648.05   630.7 2649.91
   640.7 2651.34   690.8 2655.98   720.8 2659.27   750.9 2662.95   790.9    2668
   800.9  2669.4   820.9 2672.71     851 2678.34     871 2682.45  1001.2 2715.34
#Mann= 3 , 0 , 0
       0      .1       0   590.7    .045       0   610.7      .1       0
Bank Sta=590.7,610.7
XS Rating Curve= 0 ,0
Exp/Cntr=0.3,0.1

Type RM Length L Ch R = 1 ,436.9   ,212.3,173.5,135
XS GIS Cut Line= 4
     2041295.681      394855.708     2041692.488      395256.042
      2041683.67      395381.256     2042075.186      395735.736
#Sta/Elev= 30
       0 2787.33    98.9 2753.53   187.9 2724.14   227.4 2711.53   257.1 2703.78
     356 2681.29   395.6 2671.55   415.3 2667.88   543.9 2654.27   602.3    2649
   630.9 2645.03   640.9 2644.55   650.9 2645.53   660.2 2648.54   669.9 2652.72
   679.5 2655.49   689.2 2657.15   719.1 2660.86     759 2663.34   768.9 2664.32
   858.6 2675.24   878.5 2678.72    1028 2713.42  1097.8 2728.75  1147.6  2740.2
  1157.6 2742.73  1167.5 2745.78  1187.4 2753.01  1197.4 2756.05  1217.3 2760.99
#Mann= 3 , 0 , 0
       0     .08       0   630.9    .045       0   650.9     .08       0
Bank Sta=630.9,650.9
XS Rating Curve= 0 ,0
Exp/Cntr=0.3,0.1

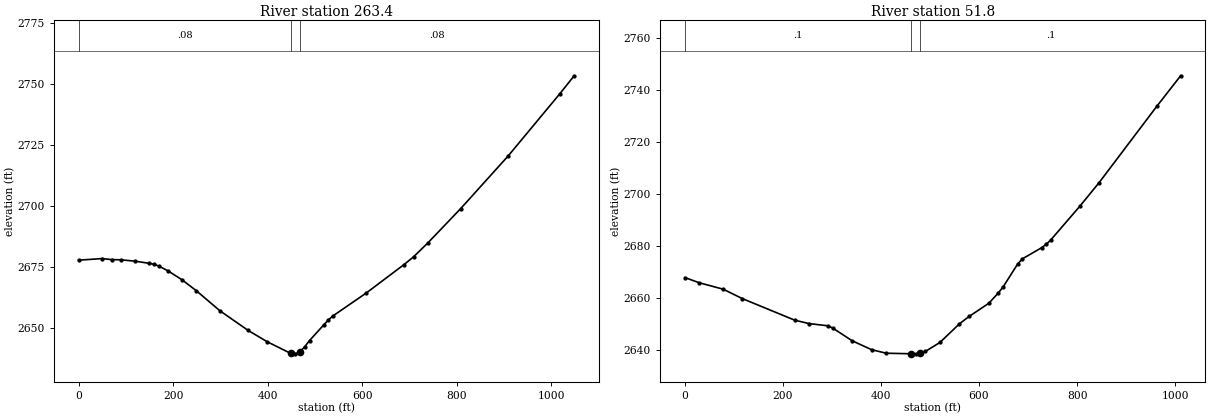
Type RM Length L Ch R = 1 ,263.4   ,205.7,211.6,217.3
XS GIS Cut Line= 3
     2041145.777      395257.805     2041636.053      395455.327
     2042025.814      395799.134
#Sta/Elev= 30
       0  2677.9    49.9 2678.56    69.8 2678.14    89.8 2678.05   119.7  2677.5
   149.6 2676.61   159.6  2676.2   169.5 2675.53   189.5 2673.51   219.4 2669.81
   249.3 2665.38   299.2 2657.16     359 2649.12   398.9 2644.53   448.8 2639.74
   458.8 2639.56   468.8 2640.46   478.7 2642.55   488.7 2645.02   518.6 2651.39
   528.6 2653.49   538.6 2655.15   608.5 2664.45   688.5 2676.11   708.5 2679.25
   738.5 2684.89   808.4 2699.04   908.4  2720.5  1018.3 2746.11  1048.3 2753.39
#Mann= 3 , 0 , 0
       0     .08       0   448.8    .045       0   468.8     .08       0
Bank Sta=448.8,468.8
XS Rating Curve= 0 ,0
Exp/Cntr=0.3,0.1

Type RM Length L Ch R = 1 ,51.8    ,52.5,51.8,51.1
XS GIS Cut Line= 4
     2041139.898      395307.479      2041370.34      395544.975
     2041612.539      395702.522      2041988.77      395810.689
#Sta/Elev= 30
       0 2667.88    29.2 2665.89    77.9 2663.43   116.8 2659.83   223.9 2651.53
   253.1 2650.22     292 2649.36   301.7 2648.46   340.9 2643.64   380.7  2640.2
   410.6 2638.84   460.4 2638.63   470.4  2638.6   480.4 2638.78   490.3  2639.5
   520.2 2642.97   560.1 2650.15     580 2652.99   619.8    2658   639.4 2661.99
   649.2 2664.34   678.6 2673.04   688.4 2675.08   727.5 2679.34   737.3 2680.68
   747.1  2682.5   805.8 2695.32     845 2704.36   962.4 2733.59  1011.3 2745.38
#Mann= 3 , 0 , 0
       0      .1       0   460.4    .045       0   480.4      .1       0
Bank Sta=460.4,480.4
XS Rating Curve= 0 ,0
Exp/Cntr=0.3,0.1

Chan Stop Cuts=-1
Use User Specified Reach Order=0
Composite Channel Slope=5